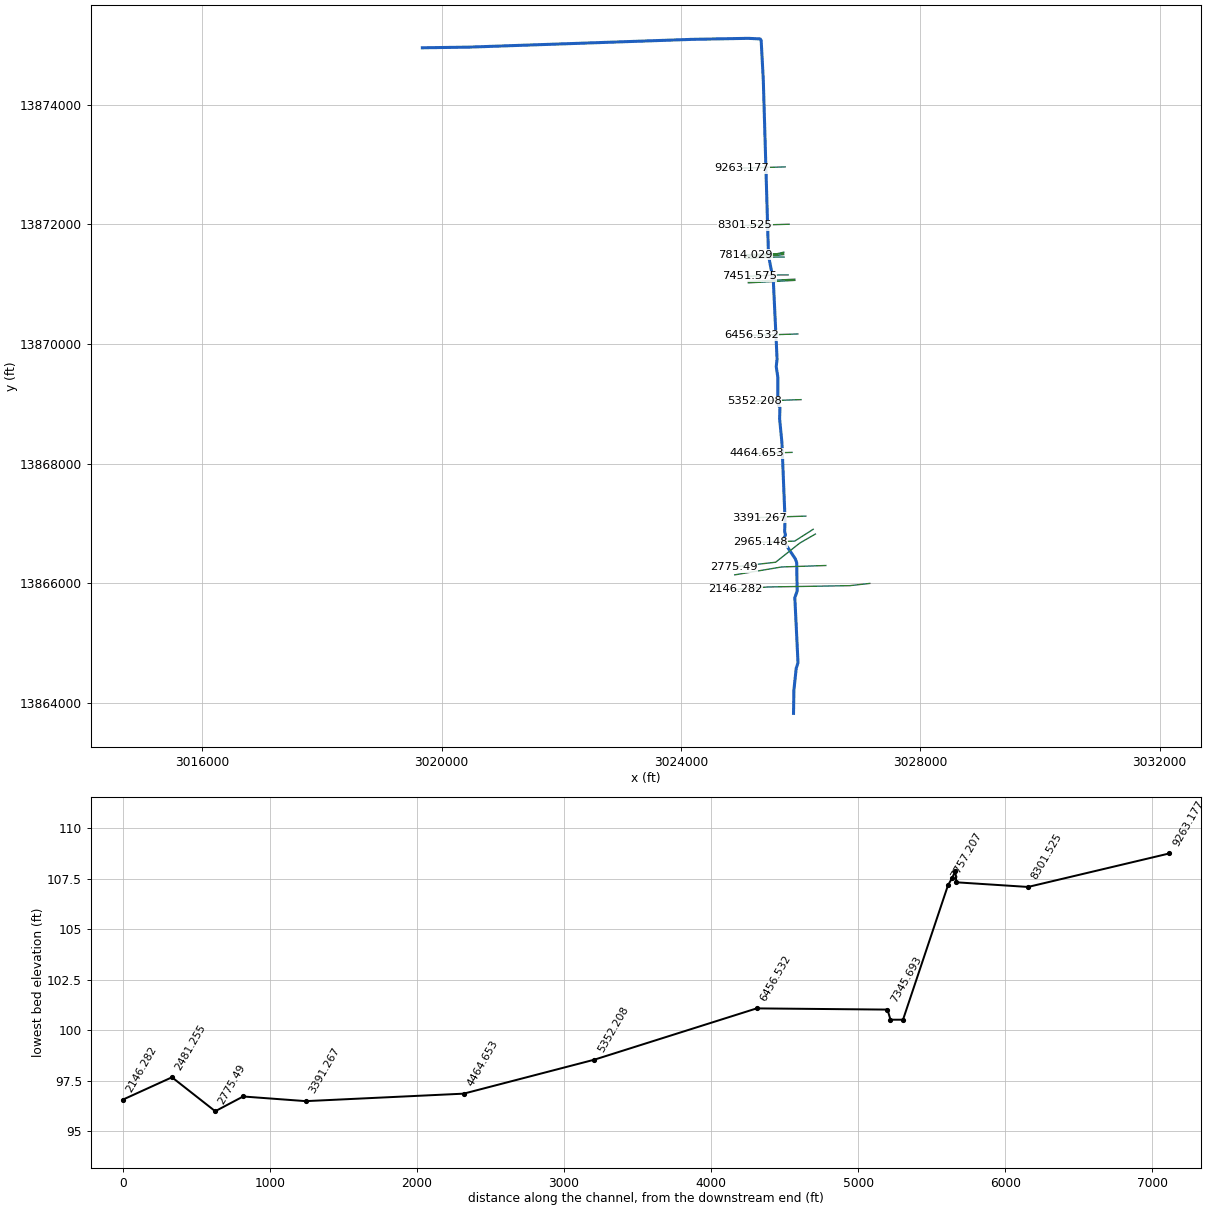
--- U102-01-00.prj (project) ---

Proj Title=U102-01-00 2019 (Re-Study)
Current Plan=p02
Default Exp/Contr=0.3,0.1
English Units
Geom File=g01
Flow File=f01
Flow File=f02
Flow File=f03
Plan File=p01
Plan File=p02
Plan File=p03
Y Axis Title=Elevation
X Axis Title(PF)=Main Channel Distance
X Axis Title(XS)=Station
BEGIN DESCRIPTION:
Tributary 4.5 to Bear Creek (U102-01-00)
(Flood Hazard & Floodway) Model
10-, 2-, 1-, and 0.2% Events
Filename U102_01_00.prj
Prepared by:  LAN                               Date: 10/29/2012
Reviewed by: HCFCD                         Date: 10/16/2012
STATUS: Final
ADDICKS WATERSHED MODEL UPDATE
HARRIS COUNTY, TEXAS
END DESCRIPTION:
DSS Export Rating Curves= 0
DSS Export Rating Curve Sorted= 0
DSS Export Volume Flow Curves= 0
DXF OffsetX= 0
DXF OffsetY= 0
DXF ScaleX= 1
DXF ScaleY= 10

--- U102-01-00.p02 (plan) ---

Plan Title=Effective Floodway 2019 (Re-Study)
Program Version=4.10
Short Identifier=Eff+ReStudy FW
Geom File=g01
Flow File=f02
Subcritical Flow
K Sum by GR= 0
Std Step Tol= 0.01
Critical Tol= 0.01
Num of Std Step Trials= 20
Max Error Tol= 0.3
Flow Tol Ratio= 0.001
Split Flow NTrial= 30
Split Flow Tol= 0.02
Split Flow Ratio= 0.02
Log Output Level= 0
Friction Slope Method= 1
Unsteady Friction Slope Method= 2
Unsteady Bridges Friction Slope Method= 1
Parabolic Critical Depth
Global Vel Dist= 0 , 0 , 0
Global Log Level= 0
CheckData=True
Encroach Param=-1 ,0,0, 2
Encroach River=U102-01-00
Encroach Reach=U102-01-00_0006
Encroach Node=9263.177
       1  288.56  368.17
Encroach Node=8301.525
       1  313.48  398.07
Encroach Node=7814.029
       1  214.63  303.92
Encroach Node=7807.646
       1  207.07  306.64
Encroach Node=7786.81
       1  177.31  321.89
Encroach Node=7757.207
       1  189.06  320.74
Encroach Node=7451.575
       1  179.13  330.31
Encroach Node=7366.426
       1  275.72  434.42
Encroach Node=7345.693
       1   286.6  430.83
Encroach Node=6456.532
       1  304.37  439.09
Encroach Node=5352.208
       1  299.38  449.07
Encroach Node=4464.653
       1   99.55  248.88
Encroach Node=3391.267
       1  229.52  444.08
Encroach Node=2965.148
       1  381.22  611.03
Encroach Node=2775.49
       1  375.97  698.14
Encroach Node=2481.255
       1  332.76  576.13
Encroach Node=2146.282
       1 1142.51 1296.97
Encroach Node=2041.704
       1 1201.11 1360.68
Encroach Node=1081.651
       1 1336.38 2039.41
Encroach Node=1032.373
       1 1457.92 2041.29
Encroach Node=919.8665
       1 1462.81 2046.17
Encroach Node=845.0081
       1 1398.69 1570.98
Encroach Node=561.271
       1 1245.07 1441.26
Computation Interval=1HOUR
Output Interval=1HOUR
Run HTab= 0
Run UNet= 0
Run PostProcess= 0
Run WQNet= 0
UNET Theta= 1
UNET Theta Warmup= 1
UNET ZTol= 0.02
UNET ZSATol= 0.05
UNET MxIter= 20
UNET MaxInSteps= 0
UNET DtIC= 0
UNET DtMin= 0
UNET MaxCRTS= 20
UNET WFStab= 2
UNET SFStab= 1
UNET WFX= 1
UNET SFX= 1
UNET DSS MLevel= 4
UNET DZMax Abort= 100
UNET Convert EG Bridges= 0
UNET Use Existing IB Tables=-1
UNET Froude Reduction=False
UNET Froude Limit= 1
UNET Froude Power= 10
UNET Time Slicing=0,0, 5
UNET Junction Losses=0
Instantaneous Interval=1HOUR
Write IC File= 0
Write IC File at Sim End=0
Echo Input=False
Echo Parameters=False
Echo Output=False
Write Detailed= 0
WQ AD Non Conservative
WQ ULTIMATE=-1
WQ Max Comp Step=1HOUR
WQ Output Interval=15MIN
WQ Output Selected Increments= 0
WQ Output face flow=0
WQ Output face velocity=0
WQ Output face area=0
WQ Output face dispersion=0
WQ Output cell volume=0
WQ Output cell surface area=0
WQ Output cell continuity=0
WQ Output cumulative cell continuity=0
WQ Output face conc=0
WQ Output face dconc_dx=0
WQ Output face courant=0
WQ Output face peclet=0
WQ Output face adv mass=0
WQ Output face disp mass=0
WQ Output cell mass=0
WQ Output cell source sink temp=0
WQ Output cell source sink nsm=0
WQ Output MaxMinRange=-1
WQ Daily Max Min Mean=-1
WQ Daily Range=0
WQ Daily Time=0
WQ Create Restart=0
WQ Fixed Restart=0
WQ System Summary=0
WQ Use Fixed Temperature=0
Sorting and Armoring Iterations= 10
XS Update Threshold= 0.02
Hydraulics Update Threshold= 0.02
Energy Slope Method= 1
Volume Change Method= 0
XS Weighting Method= 0
Number of US Weighted Cross Sections= 1
Number of DS Weighted Cross Sections= 1
Upstream XS Weight=0.25
Main XS Weight=0.5
Downstream XS Weight=0.25
Number of DS XS's Weighted with US Boundary= 1
Upstream Boundary Weight= 1
Weight of XSs Associated with US Boundary= 0
Number of US XS's Weighted with DS Boundary= 1
Downstream Boundary Weight= 0.5
Weight of XSs Associated with DS Boundary= 0.5
Sediment Output Level= 4
Mass or Volume Output= 0
Output Increment Type= 1
Profile and TS Output Increment= 10
XS Output Flag= 0
XS Output Increment= 10
Disregard all LS=0
Disregard all Conn=0
Disregard all Breaches=0
Disregard all Pumps=0

--- U102-01-00.p01 (plan) ---

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Plan Title=Effective Multi-Profile 2019 (Re-Study)
Short Identifier=Eff+ReStudy MP
Geom File=g01
Flow File=f01
Encroach Param=-1 ,0,0, 0

--- U102-01-00.p03 (plan) ---

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Plan Title=Conveyance (CO)
Short Identifier=CO
Geom File=g01
Flow File=f03
Encroach Param=-1 ,0,0, 0

--- U102-01-00.f02 (steady flow) ---

Flow Title=Effective Floodway 2019 (Re-Study)
Program Version=4.10
Number of Profiles= 2
Profile Names=100YR,FW
River Rch & RM=U102-01-00,U102-01-00_0006 ,9263.177
    1007    1007
River Rch & RM=U102-01-00,U102-01-00_0006 ,8301.525
    1068    1068
River Rch & RM=U102-01-00,U102-01-00_0006 ,7814.029
    1075    1075
River Rch & RM=U102-01-00,U102-01-00_0006 ,7757.207
    1129    1129
River Rch & RM=U102-01-00,U102-01-00_0006 ,7345.693
    1256    1256
River Rch & RM=U102-01-00,U102-01-00_0006 ,6456.532
    1433    1433
River Rch & RM=U102-01-00,U102-01-00_0006 ,5352.208
    1594    1594
River Rch & RM=U102-01-00,U102-01-00_0006 ,4464.653
    1812    1812
River Rch & RM=U102-01-00,U102-01-00_0006 ,3391.267
    1907    1907
River Rch & RM=U102-01-00,U102-01-00_0006 ,2965.148
    1951    1951
River Rch & RM=U102-01-00,U102-01-00_0006 ,2775.49
    2021    2021
River Rch & RM=U102-01-00,U102-01-00_0006 ,2481.255
    2103    2103
River Rch & RM=U102-01-00,U102-01-00_0006 ,2146.282
    2130    2130
River Rch & RM=U102-01-00,U102-01-00_0006 ,2041.704
    2389    2389
River Rch & RM=U102-01-00,U102-01-00_0006 ,1081.651
    2457    2457
River Rch & RM=U102-01-00,U102-01-00_0006 ,845.0081
    2542    2542
Boundary for River Rch & Prof#=U102-01-00,U102-01-00_0006 , 1
Up Type= 0
Dn Type= 3
Dn Slope=0.0018
Boundary for River Rch & Prof#=U102-01-00,U102-01-00_0006 , 2
Up Type= 0
Dn Type= 3
Dn Slope=0.0018
Observed WS=U102-01-00      ,U102-01-00_0006 ,9263.177,0,115.23,116.27
Observed WS=U102-01-00      ,U102-01-00_0006 ,8301.525,0,113.22,114.28
Observed WS=U102-01-00      ,U102-01-00_0006 ,7814.029,0,111.92,112.99
Observed WS=U102-01-00      ,U102-01-00_0006 ,7807.646,0,111.17,112.52
Observed WS=U102-01-00      ,U102-01-00_0006 ,7786.81 ,0,111.63,112.82
Observed WS=U102-01-00      ,U102-01-00_0006 ,7757.207,0,111.7,112.88
Observed WS=U102-01-00      ,U102-01-00_0006 ,7451.575,0,107.49,108.74
Observed WS=U102-01-00      ,U102-01-00_0006 ,7366.426,0,107.45,108.71
Observed WS=U102-01-00      ,U102-01-00_0006 ,7345.693,0,107.43,108.69
Observed WS=U102-01-00      ,U102-01-00_0006 ,6456.532,0,106.62,107.97
Observed WS=U102-01-00      ,U102-01-00_0006 ,5352.208,0,105.74,107.14
Observed WS=U102-01-00      ,U102-01-00_0006 ,4464.653,0,105.2,106.54
Observed WS=U102-01-00      ,U102-01-00_0006 ,3391.267,0,104.49,105.67
Observed WS=U102-01-00      ,U102-01-00_0006 ,2965.148,0,104.22,105.37
Observed WS=U102-01-00      ,U102-01-00_0006 ,2775.49 ,0,104,105.19
Observed WS=U102-01-00      ,U102-01-00_0006 ,2481.255,0,103.78,104.97
Observed WS=U102-01-00      ,U102-01-00_0006 ,2146.282,0,103.63,104.81
Observed WS=U102-01-00      ,U102-01-00_0006 ,2041.704,0,103.58,104.76
Observed WS=U102-01-00      ,U102-01-00_0006 ,1081.651,0,102.51,103.71
Observed WS=U102-01-00      ,U102-01-00_0006 ,1032.373,0,102.25,103.44
Observed WS=U102-01-00      ,U102-01-00_0006 ,919.8665,0,101.8,102.89
Observed WS=U102-01-00      ,U102-01-00_0006 ,845.0081,0,101.71,102.79
Observed WS=U102-01-00      ,U102-01-00_0006 ,561.271 ,0,99.72,100.68
DSS Import GetInterval= 0
DSS Import GetPeak= 0
DSS Import FillOption= 0

--- U102-01-00.f01 (steady flow) ---

Flow Title=Effective Multi-Profile 2019 (Re-Study)
Program Version=4.10
Number of Profiles= 4
Profile Names=10YR,50YR,100YR,500YR
River Rch & RM=U102-01-00,U102-01-00_0006 ,9263.177
     580     871    1007    1426
River Rch & RM=U102-01-00,U102-01-00_0006 ,8301.525
     615     923    1068    1511
River Rch & RM=U102-01-00,U102-01-00_0006 ,7814.029
     619     929    1075    1522
River Rch & RM=U102-01-00,U102-01-00_0006 ,7757.207
     650     976    1129    1598
River Rch & RM=U102-01-00,U102-01-00_0006 ,7345.693
     723    1085    1256    1778
River Rch & RM=U102-01-00,U102-01-00_0006 ,6456.532
     825    1239    1433    2029
River Rch & RM=U102-01-00,U102-01-00_0006 ,5352.208
     917    1377    1594    2256
River Rch & RM=U102-01-00,U102-01-00_0006 ,4464.653
    1043    1566    1812    2565
River Rch & RM=U102-01-00,U102-01-00_0006 ,3391.267
    1098    1648    1907    2699
River Rch & RM=U102-01-00,U102-01-00_0006 ,2965.148
    1123    1685    1951    2760
River Rch & RM=U102-01-00,U102-01-00_0006 ,2775.49
    1163    1746    2021    2859
River Rch & RM=U102-01-00,U102-01-00_0006 ,2481.255
    1210    1817    2103    2976
River Rch & RM=U102-01-00,U102-01-00_0006 ,2146.282
    1226    1840    2130    3014
River Rch & RM=U102-01-00,U102-01-00_0006 ,2041.704
    1375    2064    2389    3380
River Rch & RM=U102-01-00,U102-01-00_0006 ,1081.651
    1414    2123    2457    3477
River Rch & RM=U102-01-00,U102-01-00_0006 ,845.0081
    1463    2196    2542    3597
Boundary for River Rch & Prof#=U102-01-00,U102-01-00_0006 , 1
Up Type= 0
Dn Type= 3
Dn Slope=0.0018
Boundary for River Rch & Prof#=U102-01-00,U102-01-00_0006 , 2
Up Type= 0
Dn Type= 3
Dn Slope=0.0018
Boundary for River Rch & Prof#=U102-01-00,U102-01-00_0006 , 3
Up Type= 0
Dn Type= 3
Dn Slope=0.0018
Boundary for River Rch & Prof#=U102-01-00,U102-01-00_0006 , 4
Up Type= 0
Dn Type= 3
Dn Slope=0.0018
Observed WS=U102-01-00      ,U102-01-00_0006 ,9263.177,0,115.23,116.27,116.71,117.83
Observed WS=U102-01-00      ,U102-01-00_0006 ,8301.525,0,113.22,114.28,114.76,116.07
Observed WS=U102-01-00      ,U102-01-00_0006 ,7814.029,0,111.92,112.99,113.53,115.04
Observed WS=U102-01-00      ,U102-01-00_0006 ,7807.646,0,111.17,112.52,113.11,114.73
Observed WS=U102-01-00      ,U102-01-00_0006 ,7786.81 ,0,111.63,112.82,113.38,114.94
Observed WS=U102-01-00      ,U102-01-00_0006 ,7757.207,0,111.7,112.88,113.43,114.94
Observed WS=U102-01-00      ,U102-01-00_0006 ,7451.575,0,107.49,108.74,109.28,110.64
Observed WS=U102-01-00      ,U102-01-00_0006 ,7366.426,0,107.45,108.71,109.25,110.63
Observed WS=U102-01-00      ,U102-01-00_0006 ,7345.693,0,107.43,108.69,109.24,110.62
Observed WS=U102-01-00      ,U102-01-00_0006 ,6456.532,0,106.62,107.97,108.53,109.93
Observed WS=U102-01-00      ,U102-01-00_0006 ,5352.208,0,105.74,107.14,107.68,109.04
Observed WS=U102-01-00      ,U102-01-00_0006 ,4464.653,0,105.2,106.54,107.04,108.32
Observed WS=U102-01-00      ,U102-01-00_0006 ,3391.267,0,104.49,105.67,106.09,107.37
Observed WS=U102-01-00      ,U102-01-00_0006 ,2965.148,0,104.22,105.37,105.77,107.09
Observed WS=U102-01-00      ,U102-01-00_0006 ,2775.49 ,0,104,105.19,105.59,106.96
Observed WS=U102-01-00      ,U102-01-00_0006 ,2481.255,0,103.78,104.97,105.36,106.77
Observed WS=U102-01-00      ,U102-01-00_0006 ,2146.282,0,103.63,104.81,105.19,106.6
Observed WS=U102-01-00      ,U102-01-00_0006 ,2041.704,0,103.58,104.76,105.13,106.57
Observed WS=U102-01-00      ,U102-01-00_0006 ,1081.651,0,102.51,103.71,103.98,105.71
Observed WS=U102-01-00      ,U102-01-00_0006 ,1032.373,0,102.25,103.44,103.63,105.54
Observed WS=U102-01-00      ,U102-01-00_0006 ,919.8665,0,101.8,102.89,103.29,104.09
Observed WS=U102-01-00      ,U102-01-00_0006 ,845.0081,0,101.71,102.79,103.18,104.06
Observed WS=U102-01-00      ,U102-01-00_0006 ,561.271 ,0,99.72,100.68,101.02,101.81
DSS Import GetInterval= 0
DSS Import GetPeak= 0
DSS Import FillOption= 0

--- U102-01-00.f03 (steady flow) ---

Flow Title=Conveyance Flows
Program Version=4.10
Number of Profiles= 1
Profile Names=100YR
River Rch & RM=U102-01-00,U102-01-00_0006 ,9263.177
    3100
Boundary for River Rch & Prof#=U102-01-00,U102-01-00_0006 , 1
Up Type= 0
Dn Type= 3
Dn Slope=0.0018
DSS Import GetInterval= 0
DSS Import GetPeak= 0
DSS Import FillOption= 0

--- U102-01-00.g01 (geometry) ---

Geom Title=U102-01-00 2019 (Re-Study)
Program Version=4.10

River Reach=U102-01-00      ,U102-01-00_0006
Reach XY= 30
3019675.7475746913874948.99633473020456.5025748613874959.9979531
3024189.2529833613875089.99703693025123.7471773613875107.0035646
3025324.7461191913875097.00095993025339.2460901913875070.0003578
3025374.7499561913874416.99969533025462.0548996913871476.2798549
3025542.0698315213871063.11303043025605.2147183613869747.3371186
3025591.0743266913869620.62149283025618.7127228513869436.9335399
3025618.1776189513869103.19733083025629.4020059413868968.5027183
3025653.49382128 13868937.8403783025647.4298570313868748.1819647
3025686.0724962813868352.52133873025738.8794772813867051.6600953
3025731.4877597813866864.94918263025746.2711947713866802.8036376
3025718.6206595313866753.25124333025717.7991388613866695.7598884
3025911.4568880213866405.08494493025933.1704272813866344.1027834
3025940.87021503 13865867.7953373025901.9001486213865756.6741682
3025955.0611315213864674.25408893025925.1625692713864575.9284982
3025886.6295098713864216.40067393025880.0435650213863824.0763274

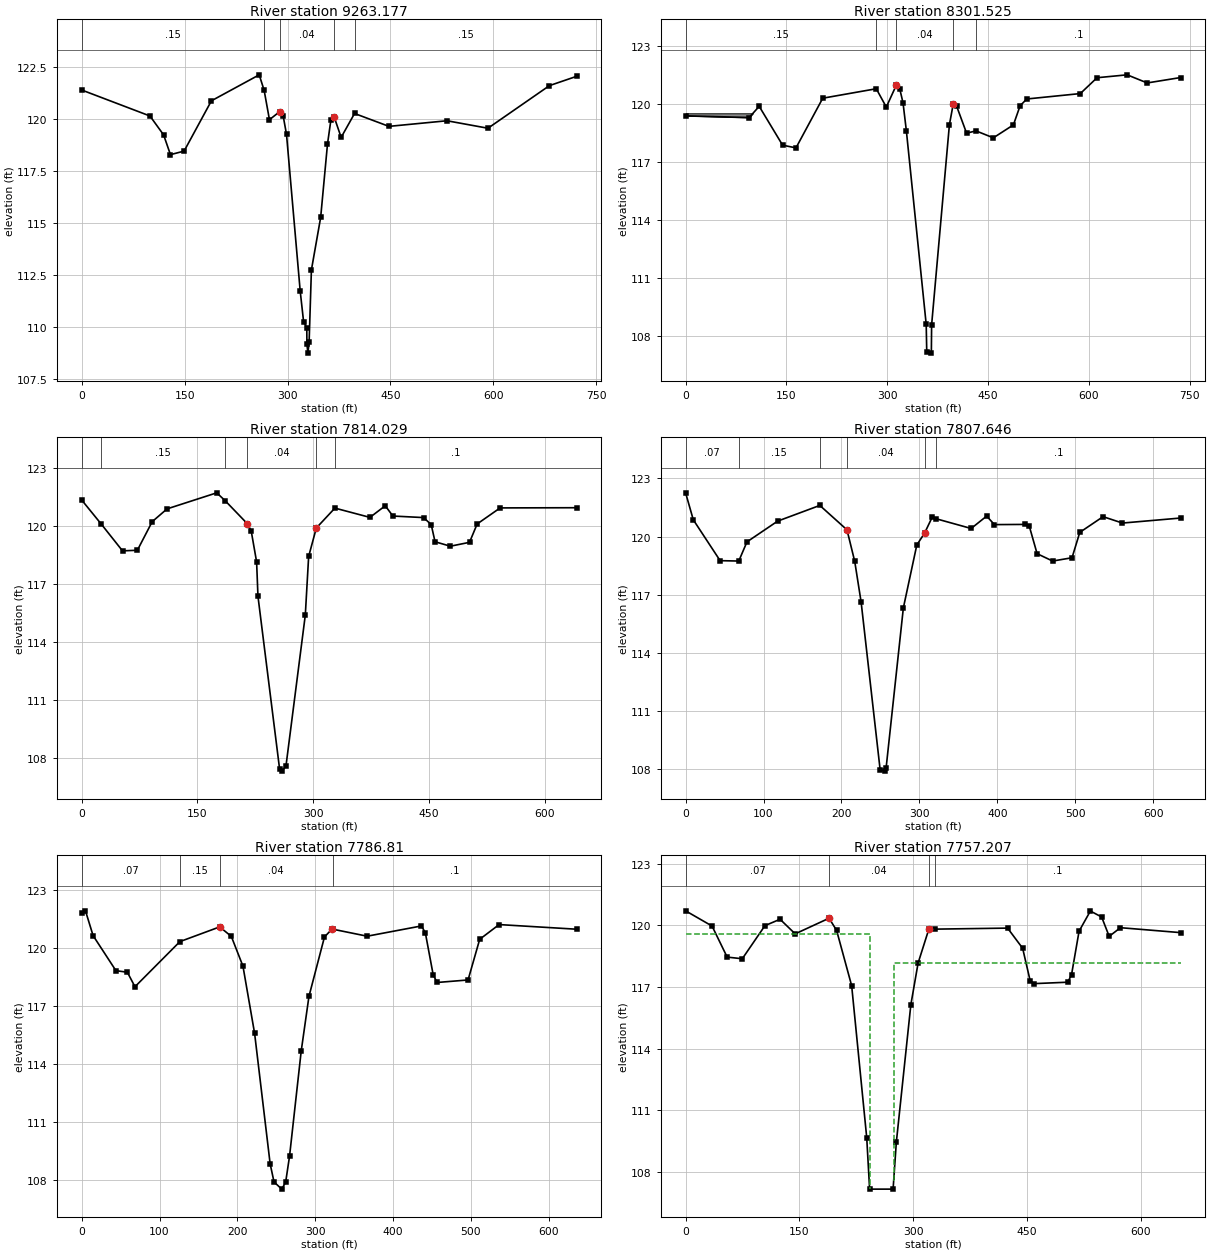
Type RM Length L Ch R = 1 ,9263.177,960.68,961.65,960.7
BEGIN DESCRIPTION:
Limit of Detailed Study
END DESCRIPTION:
Node Name=J
XS GIS Cut Line= 2
3025740.9168747813872958.14008023025019.7933170213872937.9514723
#Sta/Elev= 30
       0  121.41    99.5  120.16  119.41  119.25  129.36   118.3  149.26  118.47
  189.06  120.89  258.71  122.14  265.93  121.39  273.64  119.98  288.56  120.37
  293.54  120.18  298.51  119.27  318.41  111.75  323.39  110.26  328.04  109.98
  328.23  109.18  329.68  108.75  331.43  109.27  334.77  112.75  348.27  115.28
  358.22  118.81  363.19  119.97  368.17  120.09  378.12  119.13  397.64  120.28
  447.77  119.66  532.35  119.93  592.05  119.57   681.6  121.62  721.41  122.07
#Mann= 5 ,-1 , 0
       0     .15       0  265.93     .07       0  288.56     .04       0
  368.17     .07       0  397.64     .15       0
Bank Sta=288.56,368.17
XS Rating Curve= 0 ,0
Exp/Cntr=0.3,0.1

Type RM Length L Ch R = 1 ,8301.525,487.38,487.5,487.78
BEGIN DESCRIPTION:
Approx. 400 ft D/S of Confluence with U102-01-02
END DESCRIPTION:
XS GIS Cut Line= 2
3025806.0620856913871999.73910993025069.9260907813871978.8060808
#Sta/Elev= 30
       0  119.37   94.54  119.28  109.47  119.86   144.3  117.85   164.2  117.71
  204.01  120.28  283.63  120.77  298.55  119.82  313.48  120.96  318.46  120.78
  323.43  120.04  328.41  118.59   357.9  108.58  358.74  107.13  365.56  107.09
  365.96  108.55  392.43  118.91  398.07  119.97  403.05  119.88  417.98  118.47
  431.93  118.59  457.78  118.23  487.64   118.9  497.59  119.89  507.54  120.24
  587.16  120.52  612.04  121.34  656.82  121.49  686.67  121.07  736.43  121.35
#Mann= 5 ,-1 , 0
       0     .15       0  283.63     .07       0  313.48     .04       0
  398.07     .07       0  431.93      .1       0
#Block Obstruct= 2 , 0
       0  109.47   119.5               0
Bank Sta=313.48,398.07
XS Rating Curve= 0 ,0
Exp/Cntr=0.3,0.1

Type RM Length L Ch R = 1 ,7814.029,6.8,6.38,6.81
XS GIS Cut Line= 3
3025717.4077354413871533.01596193025604.9289577813871507.1121424
3025079.4198381913871489.3490545
#Sta/Elev= 30
       0  121.34   25.45  120.09    52.9  118.71   72.14  118.74   91.38  120.22
  110.61  120.88  174.95  121.71  185.67  121.31  214.63  120.11  219.59  119.74
  226.59  118.14  228.34  116.36  256.33  107.44  259.39  107.32  264.61  107.58
  289.67  115.39     294  118.42  303.92  119.89  327.99  120.92  373.37  120.44
  393.21  121.04  403.13  120.51  442.81  120.43  452.73  120.07   457.7  119.18
  477.54  118.95  502.34  119.15  512.26   120.1  542.02  120.93  641.23  120.94
#Mann= 6 ,-1 , 0
       0     .07       0   25.45     .15       0  185.67     .07       0
  214.63     .04       0  303.92     .07       0  327.99      .1       0
Bank Sta=214.63,303.92
XS Rating Curve= 0 ,0
Exp/Cntr=0.3,0.1

Type RM Length L Ch R = 1 ,7807.646,23.95,20.84,24.14
XS GIS Cut Line= 4
3025713.3483603613871513.73384833025610.8508619413871500.4500822
3025542.00487103 13871498.9691143025079.3289591113871481.2030734
#Sta/Elev= 30
       0  122.26    9.84  120.87   44.29  118.76   68.22  118.74   78.75  119.73
  118.11   120.8  172.22  121.61  207.07  120.35  217.02  118.72   225.2  116.63
  249.58  107.98  255.79   107.9  257.24  108.05   279.4  116.32  296.68  119.57
  306.64  120.18   316.6  121.02   321.6  120.92  366.39  120.42   386.3  121.06
  396.26  120.62  436.09  120.63  441.07  120.53  451.02  119.12  470.94  118.74
  495.83  118.91  505.79  120.22  535.66  121.03  560.55   120.7  635.23  120.96
#Mann= 6 ,-1 , 0
       0     .07       0   68.22     .15       0  172.22     .07       0
  207.07     .04       0  306.64     .07       0   321.6      .1       0
Bank Sta=207.07,306.64
XS Rating Curve= 0 ,0
Exp/Cntr=0.3,0.1

Type RM Length L Ch R = 1 ,7786.81 ,30.39,29.6,30.6
XS GIS Cut Line= 3
3025715.37821195 13871492.4218833025603.7120966913871478.8280782
3025080.3929333513871464.8730536
#Sta/Elev= 30
       0  121.79    4.89  121.92   14.67  120.64   44.02  118.83   58.69  118.75
   68.47     118  126.17  120.33  177.31  121.09  192.26   120.6  207.22  119.06
  222.18  115.59  242.12  108.86  247.11  107.92  257.08  107.55  262.06  107.91
  267.05  109.25  282.01  114.67  291.98   117.5  311.92  120.57  321.89  120.99
   322.8  120.97  366.76  120.61  436.57  121.14  441.55  120.78  451.52  118.63
  456.51  118.22  496.39  118.35  511.35  120.45  536.28  121.21     636  120.97
#Mann= 4 ,-1 , 0
       0     .07       0  126.17     .15       0  177.31     .04       0
   322.8      .1       0
#XS Ineff= 2 ,-1
       0  182.26  119.59  338.11     636  118.17
Permanent Ineff=
       F       F
Bank Sta=177.31,321.89
XS Rating Curve= 0 ,0
Exp/Cntr=0.5,0.3

Type RM Length L Ch R = 1 ,7757.207,314.91,305.63,304.16
BEGIN DESCRIPTION:
Upstream Section (KEITH HARROW BLVD)
END DESCRIPTION:
Node Name=I
XS GIS Cut Line= 5
3025723.3755712813871450.82518143025583.9493409413871450.8251814
3025464.9403926113871445.58076933025388.4749943613871442.2110254
3025071.45659953 13871428.240909
#Sta/Elev= 30
       0   120.7   34.86  119.96   54.77  118.45   74.69  118.37  104.57  119.98
  124.49  120.29  144.39  119.58  189.06  120.34  198.99  119.75  218.84  117.06
   238.7  109.67  242.51  107.17  273.44  107.17  277.69  109.44  296.82  116.13
  306.39  118.16  320.74  119.83  328.94  119.81  424.34  119.86  444.17  118.88
  454.09   117.3  459.05  117.16  503.67  117.23  508.63   117.6  518.54  119.71
  533.42  120.69  548.29   120.4  558.21  119.46  573.08  119.88  652.42  119.64
#Mann= 4 ,-1 , 0
       0     .07       0  189.06     .04       0  320.74     .07       0
  328.94      .1       0
#XS Ineff= 2 ,-1
       0  243.21  119.59  274.14  652.42  118.17
Permanent Ineff=
       F       F
Bank Sta=189.06,320.74
XS Rating Curve= 0 ,0
Exp/Cntr=0.5,0.3

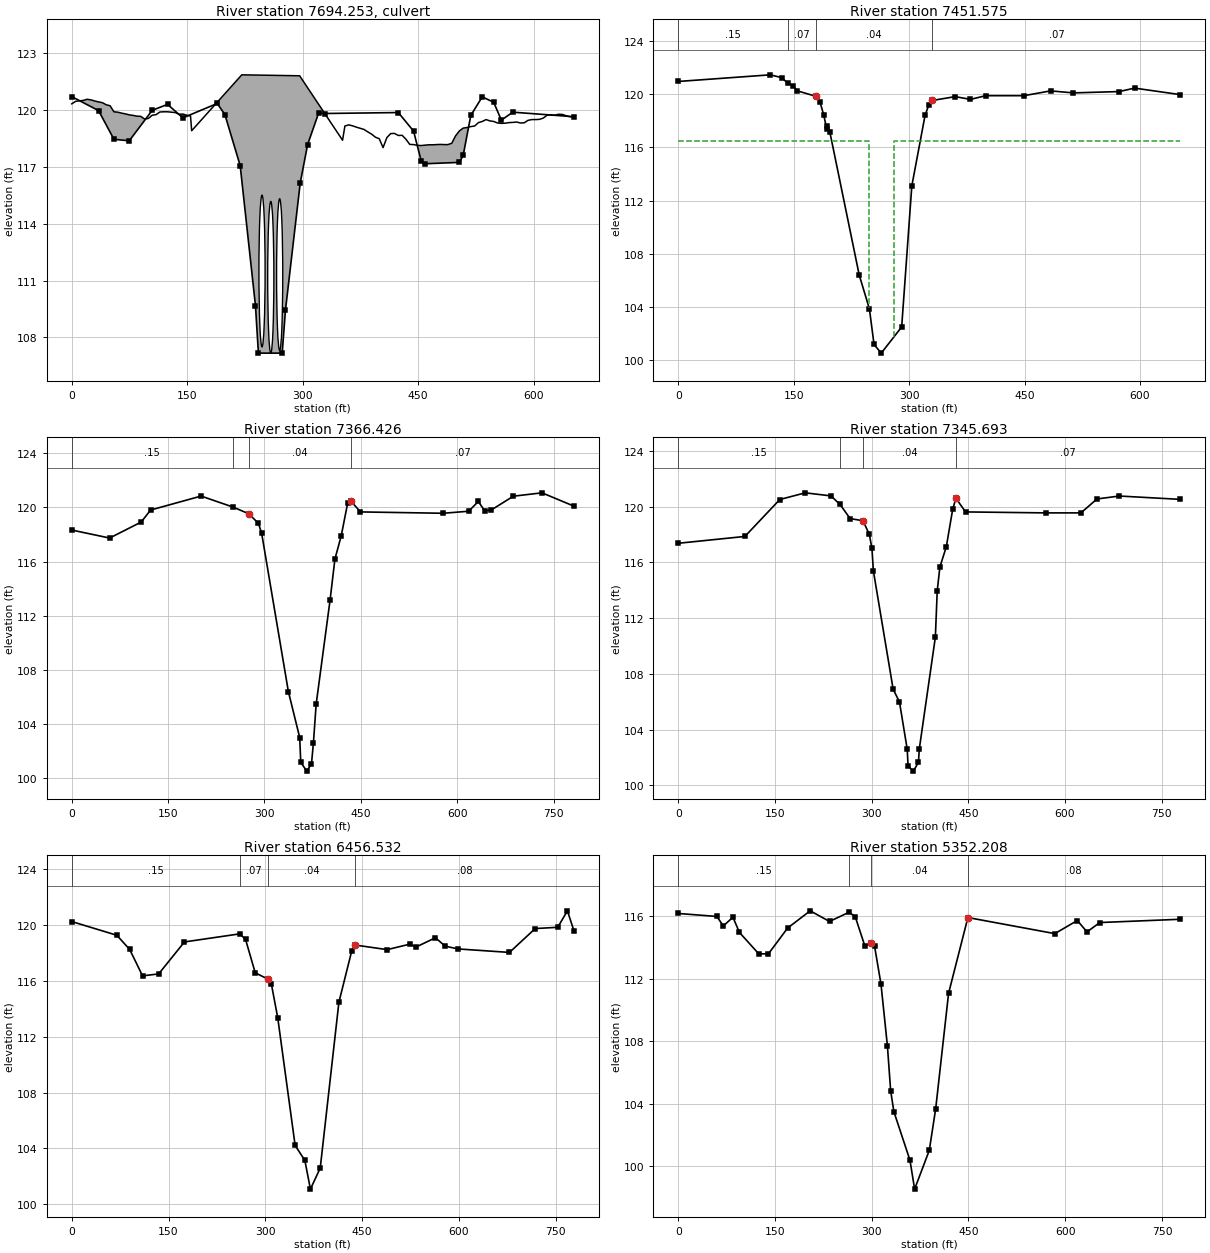
Type RM Length L Ch R = 2 ,7694.253,,,
BEGIN DESCRIPTION:
KEITH HARROW BLVD
END DESCRIPTION:
Node Name=KEITH HARROW
Bridge Culvert--1,0,-1,-1, 0
Deck Dist Width WeirC Skew NumUp NumDn MinLoCord MaxHiCord MaxSubmerge Is_Ogee
22,230,2.6,0, 97, 88, , , 0.98, 0, 0,0,,
       0    4.98    9.96   14.94   19.92    24.9   29.88   34.86   39.84   44.82
    49.8   54.77   59.75   64.73   69.71   74.69   79.67   84.65   89.63   94.61
   99.59  104.57  109.55  114.53  119.51  124.49  129.47  134.45  139.43  144.39
  149.35  154.32 155.785 220.925 296.105 351.875  354.92  359.88  364.84   369.8
  374.76  379.71  384.67  389.63  394.59  399.55  404.51  409.46  414.42  419.38
  424.34   429.3  434.26  439.21  444.17  449.13  454.09  459.05     464  468.96
  473.92  478.88  483.84   488.8  493.75  498.71  503.67  508.63  513.59  518.54
   523.5  528.46  533.42  538.38  543.34  548.29  553.25  558.21  563.17  568.13
  573.08  578.04     583  587.96  592.92  597.88  602.83  607.79  612.75  617.71
  622.67  627.62  632.58  637.54   642.5  647.46  652.42
  120.32  120.45  120.48   120.5  120.56  120.53  120.47  120.42  120.38  120.27
  120.22   119.9  119.88  119.83  119.79  119.74  119.71  119.67  119.66  119.52
  119.55  119.72  119.75  119.89   119.9   119.9  119.88  119.86  119.77  119.78
  119.72  119.68   118.9  121.85   121.8   118.4  119.15  119.21  119.16  119.09
  119.03  118.97  118.84  118.72  118.56  118.48  118.01  118.54  118.75  118.76
  118.65  118.66  118.45  118.18  118.17  118.13  118.12  118.14  118.16  118.16
  118.17  118.18  118.17  118.17  118.24  118.63  118.89  119.04  119.07  119.12
  119.15  119.33  119.39  119.49  119.42  119.39  119.31  119.29   119.3  119.33
  119.34  119.36  119.31  119.32  119.45  119.49  119.49   119.5  119.57  119.72
  119.74  119.72  119.77  119.76  119.69  119.64  119.65
                                                                                
                                                                                
                                                                                
                                                                                
                                                                                
                                                                                
                                                                                
                                                                                
                                                                                
                                                        
       0    4.98    9.96   14.94   19.92    24.9   29.88   34.86   39.84   44.82
    49.8   54.77   59.75   64.73   69.71   74.69   79.67   84.65   89.63   94.61
   99.59  104.57  109.55  114.53  119.51  124.49  129.47  134.45  139.43  144.39
  149.35  154.32  157.58  311.62  393.88  394.59  399.55  404.51  409.46  414.42
  419.38  424.34   429.3  434.26  439.21  444.17  449.13  454.09  459.05     464
  468.96  473.92  478.88  483.84   488.8  493.75  498.71  503.67  508.63  513.59
  518.54   523.5  528.46  533.42  538.38  543.34  548.29  553.25  558.21  563.17
  568.13  573.08  578.04     583  587.96  592.92  597.88  602.83  607.79  612.75
  617.71  622.67  627.62  632.58  637.54   642.5  647.46  652.42
  120.32  120.45  120.48   120.5  120.56  120.53  120.47  120.42  120.38  120.27
  120.22   119.9  119.88  119.83  119.79  119.74  119.71  119.67  119.66  119.52
  119.55  119.72  119.75  119.89   119.9   119.9  119.88  119.86  119.77  119.78
  119.72  119.68  118.93  118.69  118.38  118.56  118.48  118.01  118.54  118.75
  118.76  118.65  118.66  118.45  118.18  118.17  118.13  118.12  118.14  118.16
  118.16  118.17  118.18  118.17  118.17  118.24  118.63  118.89  119.04  119.07
  119.12  119.15  119.33  119.39  119.49  119.42  119.39  119.31  119.29   119.3
  119.33  119.34  119.36  119.31  119.32  119.45  119.49  119.49   119.5  119.57
  119.72  119.74  119.72  119.77  119.76  119.69  119.64  119.65
                                                                                
                                                                                
                                                                                
                                                                                
                                                                                
                                                                                
                                                                                
                                                                                
                                                                
BR Coef=-1 , 0 , 0 ,, 0 ,,,0.8,0,,0,
WSPro=,,,, 1 ,,,, 0 ,,,, 0 ,,,,-1 ,-1 ,-1 , 0 , 0 , 0 , 0 , 0
Culvert=1,8,,300,0.024,0.5,1,2,1,107.5,247.21,102.56,252.1,Culvert #1  , 0 ,1.7
Culvert Bottom n=0.024
Culvert=1,8,,300,0.024,0.5,1,2,1,107.17,258.6,102.16,263.59,Culvert #2  , 0 ,1.7
Culvert Bottom n=0.024
Culvert=1,8,,300,0.024,0.5,1,2,1,107.31,270.14,102.49,275.92,Culvert #3  , 0 ,1.7
Culvert Bottom n=0.024
BC Design=,, 0 ,, 0 ,,,,,,
BC Use User HTab Curves=0
BC User HTab FreeFlow(D)= 0

Type RM Length L Ch R = 1 ,7451.575,84.71,85.15,91.93
BEGIN DESCRIPTION:
Downstream Section (KEITH HARROW BLVD)
END DESCRIPTION:
XS GIS Cut Line= 5
3025790.4630355213871152.7339141 3025651.036805213871152.7339141
3025532.02785686 13871147.489502 3025455.562458613871144.1197581
3025138.5440637813871130.1496417
#Sta/Elev= 30
       0  120.97  119.51  121.47  134.45  121.26  142.67  120.82  149.35  120.64
  154.32  120.27  179.13  119.85   184.1  119.44  189.06  118.45  192.96   117.4
  193.56  117.63  196.98  117.17  235.17   106.4  248.43  103.85  254.44  101.17
  263.81  100.52  290.34  102.49  303.51   113.1  320.74  118.42  325.52  119.19
  330.31  119.54  359.88  119.83  379.71  119.62  399.55   119.9  449.13   119.9
  483.84  120.26  513.59  120.11  573.08  120.21  592.92  120.47  652.42  119.98
#Mann= 4 ,-1 , 0
       0     .15       0  142.67     .07       0  179.13     .04       0
  330.31     .07       0
#XS Ineff= 2 ,-1
       0   248.1   116.5  279.92  652.42   116.5
Permanent Ineff=
       F       F
Bank Sta=179.13,330.31
XS Rating Curve= 0 ,0
Exp/Cntr=0.5,0.3

Type RM Length L Ch R = 1 ,7366.426,20.61,20.73,20.82
Node Name=H
XS GIS Cut Line= 3
3025902.0733766113871081.38924053025701.0006160313871071.1071088
3025121.5250689413871041.4749503
#Sta/Elev= 30
       0  118.33   58.93  117.74  108.03  118.92  122.77  119.81  201.34  120.84
  250.85  120.03  275.72  119.53   290.6  118.82  295.56   118.1  337.17   106.4
  354.82     103  356.44  101.17  365.81  100.52  373.17  101.06  376.18  102.62
  380.44  105.47  402.04  113.14  409.62  116.18  419.54  117.92  429.46  120.32
  434.42  120.48   449.3  119.67  578.24  119.57  617.91  119.72  632.79  120.44
  642.71  119.76  652.63   119.8  687.34  120.83  731.98  121.08  781.57   120.1
#Mann= 4 ,-1 , 0
       0     .15       0  250.85     .07       0  275.72     .04       0
  434.42     .07       0
Bank Sta=275.72,434.42
XS Rating Curve= 0 ,0
Exp/Cntr=0.3,0.1

Type RM Length L Ch R = 1 ,7345.693,890.27,889.16,907.79
XS GIS Cut Line= 3
3025903.0887945313871061.45391293025716.2190895213871051.4969119
3025125.2271612713871020.0071454
#Sta/Elev= 30
       0  117.37  103.42  117.86  157.59  120.51  197.08  120.99  236.87  120.77
  250.98  120.16  266.71  119.14   286.6  118.99  296.55     118  300.52     117
  302.75  115.39  333.46  106.89  343.22  105.99  355.29  102.58  356.57  101.38
  364.87  101.02  372.75  101.66   373.9  102.58  398.92  110.63  401.82  113.96
  405.96  115.67  415.91  117.12  425.86  119.82  430.83   120.6  445.75  119.62
  570.08  119.55  624.79  119.55  649.66  120.55  684.47  120.76  778.96  120.52
#Mann= 4 ,-1 , 0
       0     .15       0  250.98     .07       0   286.6     .04       0
  430.83     .07       0
Bank Sta=286.6,430.83
XS Rating Curve= 0 ,0
Exp/Cntr=0.3,0.1

Type RM Length L Ch R = 1 ,6456.532,1099.73,1104.32,1100.24
Node Name=G
XS GIS Cut Line= 2
3025952.5919763613870165.89894553025174.5899234413870141.4770783
#Sta/Elev= 30
       0  120.25   69.86  119.27   89.81  118.25  109.77  116.36  134.72   116.5
  174.64  118.79  260.48  119.37  269.44  118.97  284.41  116.58  304.37  116.12
  309.36   115.8  319.34  113.35  346.28  104.21  361.34  103.14     370  101.08
   385.2  102.59  414.14  114.47   434.1  118.16  439.09  118.57  488.99  118.24
  523.91  118.63  533.89  118.43  563.83  119.09   578.8  118.49  598.76  118.29
  678.59  118.04  718.51  119.75  753.44  119.84  768.41  121.02  778.38  119.61
#Mann= 4 ,-1 , 0
       0     .15       0  260.48     .07       0  304.37     .04       0
  439.09     .08       0
Bank Sta=304.37,439.09
XS Rating Curve= 0 ,0
Exp/Cntr=0.3,0.1

Type RM Length L Ch R = 1 ,5352.208,877.24,887.56,877.57
Node Name=F
XS GIS Cut Line= 2
3026006.0659507813869068.07010443025228.0638978613869043.6479092
#Sta/Elev= 30
       0  116.19   59.88     116   69.86  115.39   84.82  115.95    94.8  114.98
  124.74  113.61  139.71   113.6  169.65  115.26  204.58  116.36  234.51  115.68
  264.91  116.27  274.43  115.98   289.4   114.1  299.38  114.33  304.37   114.1
  314.35  111.66  324.33  107.69  329.32  104.84  334.31   103.5  359.26  100.39
  366.48   98.54  389.19  101.02  399.17   103.7  419.13  111.08  449.07  115.93
  583.79   114.9  618.72  115.74  633.69  115.01  653.64  115.61  778.38  115.82
#Mann= 4 ,-1 , 0
       0     .15       0  264.91     .07       0  299.38     .04       0
  449.07     .08       0
Bank Sta=299.38,449.07
XS Rating Curve= 0 ,0
Exp/Cntr=0.3,0.1

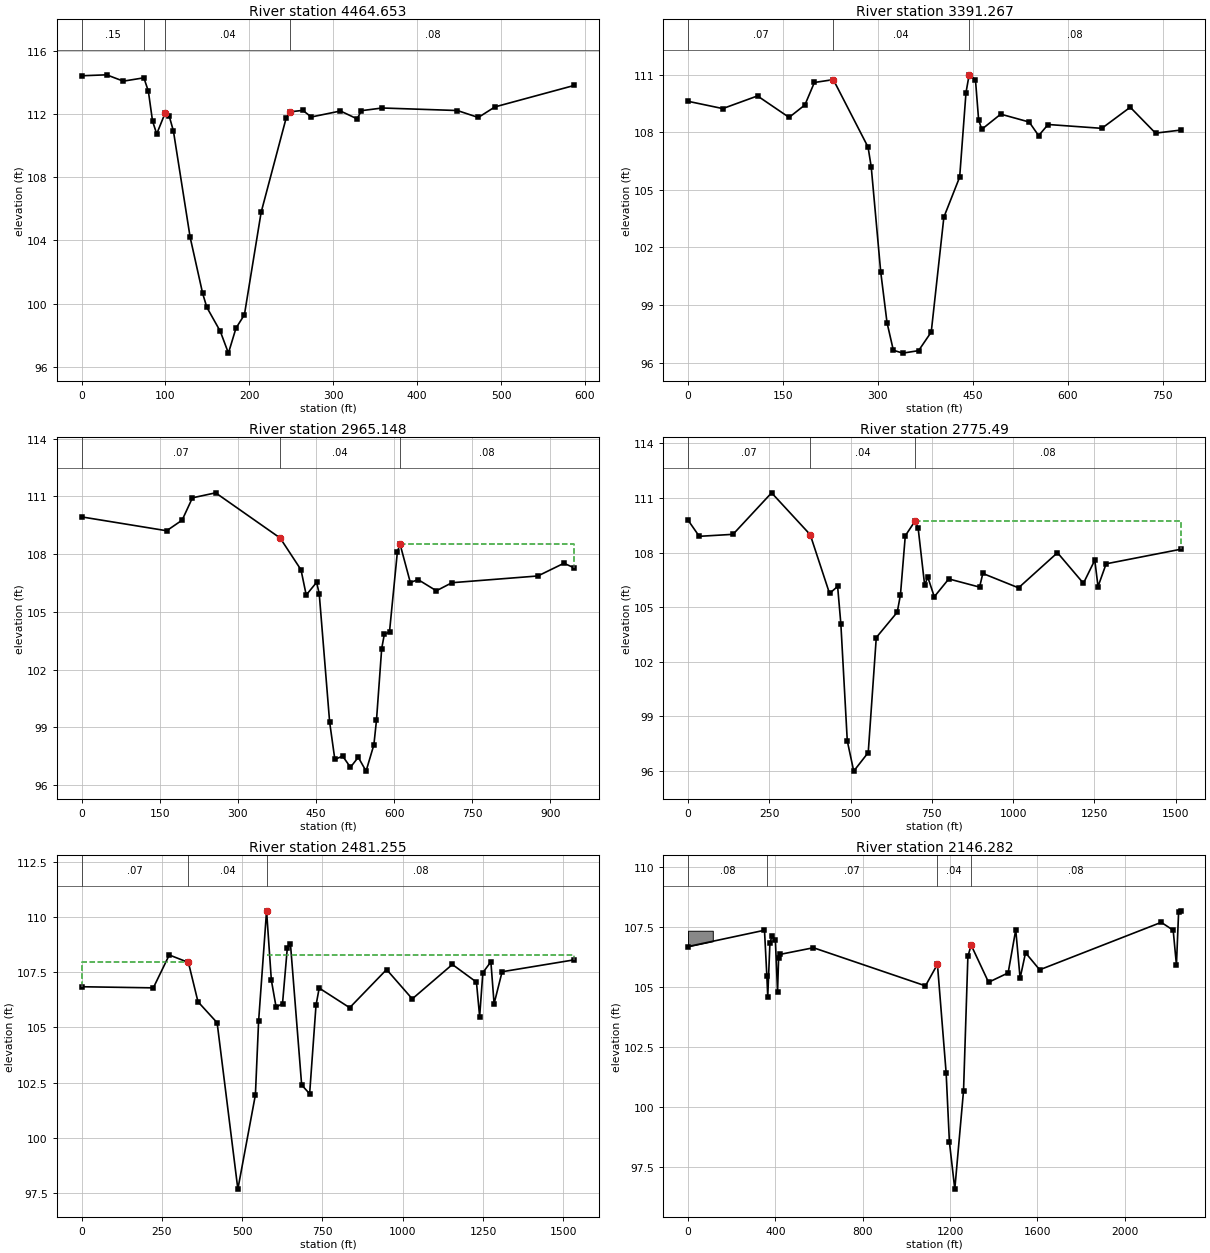
Type RM Length L Ch R = 1 ,4464.653,1072.57,1073.39,1073.98
Node Name=E
XS GIS Cut Line= 2
3025854.6617260313868186.4511328 3025267.5828477  13868168.02302
#Sta/Elev= 30
       0  114.42   29.87  114.48   49.78  114.08   74.29  114.29   79.64  113.44
   84.62  111.55    89.6  110.74   99.55  112.05  104.53  111.86  109.51  110.92
  129.42   104.2  144.35  100.64  149.33   99.76  165.37   98.24  175.07   96.86
  184.07   98.44  194.13   99.29  214.04  105.77  243.91  111.75  248.88  112.14
  263.82  112.23  273.77  111.81  308.62  112.19  328.53  111.69  333.51  112.21
  358.39  112.38  447.99  112.22  472.88  111.78  492.79  112.45  587.37  113.81
#Mann= 4 ,-1 , 0
       0     .15       0   74.29     .07       0   99.55     .04       0
  248.88     .08       0
Bank Sta=99.55,248.88
XS Rating Curve= 0 ,0
Exp/Cntr=0.3,0.1

Type RM Length L Ch R = 1 ,3391.267,411.98,426.12,412.77
XS GIS Cut Line= 2
3026086.3079162813867121.32202943025308.3058633713867096.9001623
#Sta/Elev= 30
       0  109.62   54.89  109.24  109.77   109.9  159.67  108.78  184.62  109.43
  199.59   110.6  229.52  110.75  284.41  107.23   289.4   106.2  304.37  100.73
  314.35   98.08  324.33   96.64   339.3   96.49  364.24   96.62   384.2   97.59
  404.16  103.58  429.11  105.67  439.09  110.07  444.08     111  454.06  110.74
  459.05  108.65  464.04  108.16  493.98  108.95  538.88  108.54  553.85  107.83
  568.82  108.41  653.64  108.21  698.55  109.31  738.47  107.96  778.38  108.12
#Mann= 3 ,-1 , 0
       0     .07       0  229.52     .04       0  444.08     .08       0
Bank Sta=229.52,444.08
XS Rating Curve= 0 ,0
Exp/Cntr=0.3,0.1

Type RM Length L Ch R = 1 ,2965.148,149.25,189.66,223.21
XS GIS Cut Line= 3
3026208.90937711 13866900.8838223025900.2600600313866703.7460929
3025321.1201421913866682.8130639
#Sta/Elev= 30
       0  109.93  163.32  109.21  193.02  109.76  212.81  110.92  257.35  111.18
  381.22  108.83  421.19  107.18  431.18  105.87  451.16  106.53  456.16  105.94
  476.14   99.27  486.13   97.33  501.12    97.5  516.11   96.92   531.1   97.44
  546.08   96.72  561.07   98.09  566.07   99.37  576.06  103.09  581.06  103.82
  591.05  103.96  606.04  108.08  611.03  108.54  631.01  106.52     646  106.67
  680.97  106.09  710.95  106.51  875.81  106.86  925.77  107.52  945.75  107.28
#Mann= 3 ,-1 , 0
       0     .07       0  381.22     .04       0  611.03     .08       0
#XS Ineff= 2 , 0
       0                  611.03       0  108.54
Permanent Ineff=
       F       F
#Block Obstruct= 2 , 0
       0                  925.77       0  107.52
Bank Sta=381.22,611.03
XS Rating Curve= 0 ,0
Exp/Cntr=0.3,0.1

Type RM Length L Ch R = 1 ,2775.49 ,325.58,294.23,276.53
Node Name=D
XS GIS Cut Line= 4
3026245.9371901913866821.53883633025984.8396152713866670.5401226
3025580.8604363713866350.34784963024886.49109019  13866271.41264
#Sta/Elev= 30
       0  109.78   34.61  108.89  138.45     109  257.12  111.28  375.97  108.98
  435.44  105.75  460.23  106.14  470.14  104.09  489.97   97.65  509.79   95.99
   554.4   97.01  579.18  103.33  643.62  104.72  653.53  105.68   668.4  108.92
  698.14  109.72  708.05  109.33  727.88  106.22  737.79  106.64  757.62  105.57
  802.23  106.55  896.97   106.1  906.95  106.85 1016.77  106.06 1136.57  107.99
 1216.44  106.31 1251.38  107.58 1261.36  106.13 1286.32  107.38 1515.94  108.18
#Mann= 3 ,-1 , 0
       0     .07       0  375.97     .04       0  698.14     .08       0
#XS Ineff= 2 , 0
       0  375.97  108.98  698.14       0  109.72
Permanent Ineff=
       F       F
Bank Sta=375.97,698.14
XS Rating Curve= 0 ,0
Exp/Cntr=0.3,0.1

Type RM Length L Ch R = 1 ,2481.255,335.95,334.97,334.5
XS GIS Cut Line= 3
 3026420.090057113866295.5569487 3025680.465880213866271.1350815
3024897.0704653613866139.1711066
#Sta/Elev= 30
       0  106.84   223.5  106.79  273.16  108.28  332.76  107.94  362.56  106.16
  422.16  105.21  486.73   97.67  541.36  101.94   551.3  105.27  576.13  110.28
  591.03  107.14  605.93  105.91   625.8  106.08   640.7  108.59  650.63  108.76
  685.39  102.39  710.23  101.99  730.09     106  740.03  106.78  834.96  105.89
  949.88  107.62 1029.82  106.29 1154.73  107.85 1229.68  107.05 1239.67  105.49
 1249.66  107.48 1274.65  107.97 1284.64  106.07 1309.62  107.52 1534.46  108.06
#Mann= 3 ,-1 , 0
       0     .07       0  332.76     .04       0  576.13     .08       0
#XS Ineff= 2 , 0
       0  332.76  107.94  576.13       0  108.28
Permanent Ineff=
       F       F
Bank Sta=332.76,576.13
XS Rating Curve= 0 ,0
Exp/Cntr=0.3,0.1

Type RM Length L Ch R = 1 ,2146.282,102.95,104.58,103.55
Node Name=C
XS GIS Cut Line= 4
3027155.7608298713865996.34986993026822.5196984413865958.8049975
3025452.5099712813865936.69743023024902.3601529413865895.8461339
#Sta/Elev= 30
       0  106.68   350.3  107.36  361.17  105.44  365.24  104.59  375.21  106.83
  385.17  107.13  400.12  106.94  410.09   104.8  415.07  106.21  420.05  106.35
  574.51  106.63 1087.71  105.04 1142.51  105.94 1182.37  101.41 1197.32   98.53
 1222.01   96.56 1262.09  100.67 1282.02  106.27 1296.97  106.74 1376.69  105.19
 1466.38  105.58 1501.25  107.38 1521.18  105.36  1546.1  106.42 1610.87  105.71
 2167.74  107.69 2222.41  107.36 2237.32  105.91 2247.26  108.12  2257.2  108.17
#Mann= 4 ,-1 , 0
       0     .08       0  361.17     .07       0 1142.51     .04       0
 1296.97     .08       0
#XS Ineff= 2 ,-1
       0 1142.51  105.94 1296.97  2257.2  106.74
Permanent Ineff=
       F       F
#Block Obstruct= 2 , 0
       0  113.43  107.34               0
Bank Sta=1142.51,1296.97
XS Rating Curve= 0 ,0
Exp/Cntr=0.3,0.1