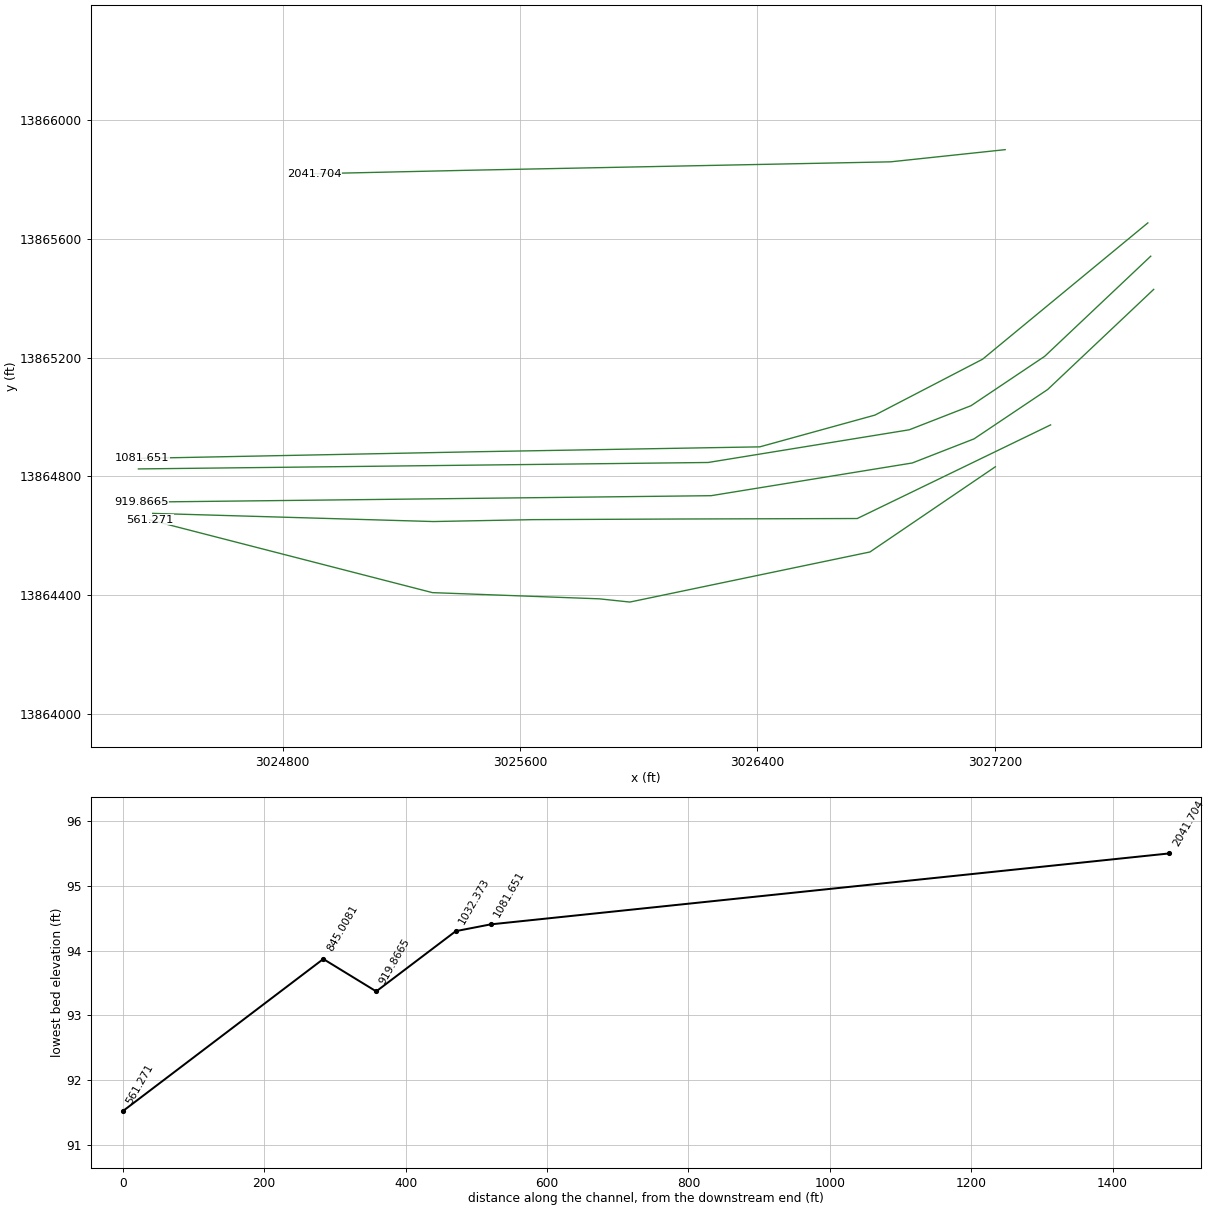
HEC-RAS study U102-01-00.prj: U102-01-00 2019 (Re-Study)

--- U102-01-00.g01 (geometry) --- (continued)

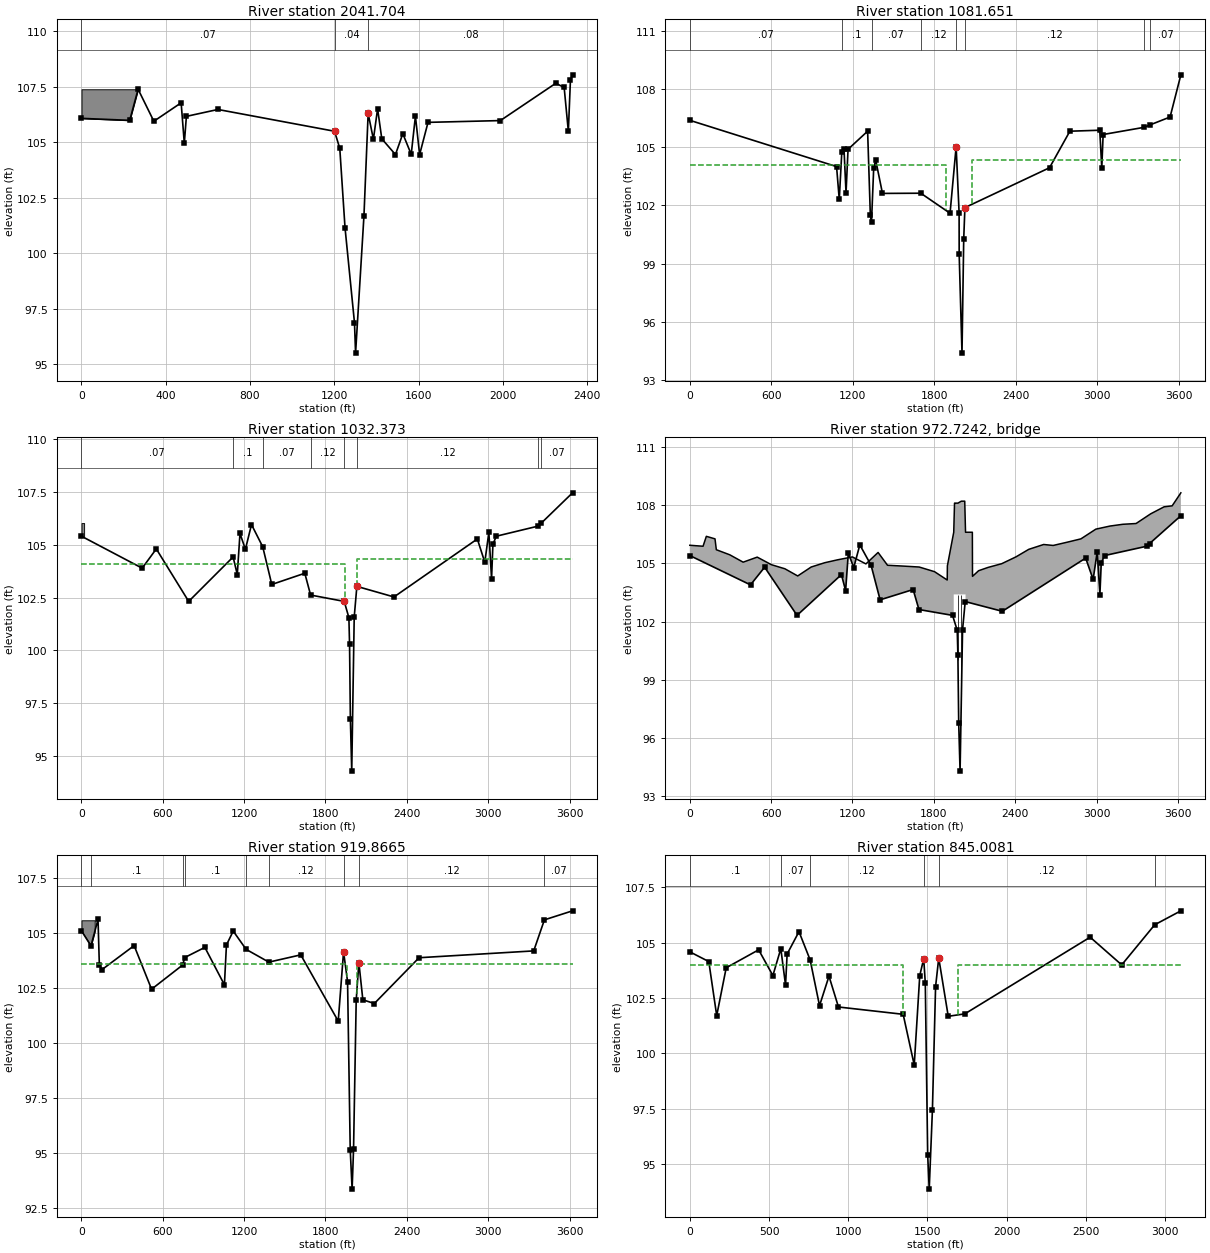
Type RM Length L Ch R = 1 ,2041.704,972.04,960.05,991.98
XS GIS Cut Line= 4
3027235.1058155313865901.13582153026848.9340156913865860.1057198
3025428.1179596913865831.70715463024906.9090283713865819.9919549
#Sta/Elev= 30
       0  106.07  229.02  105.98  268.85  107.38  343.54  105.94  473.11  106.77
  488.07  104.95  498.04  106.16  647.63  106.47 1201.11  105.49 1226.05  104.72
 1250.98  101.14 1295.85   96.87 1301.02    95.5 1340.73  101.67 1360.68  106.29
 1385.61  105.13 1405.55   106.5  1425.5  105.15 1490.32  104.44 1525.22  105.38
 1565.12  104.45 1585.06  106.17 1605.01  104.44  1644.9  105.89 1988.19  105.97
 2251.34  107.65 2291.06  107.46 2310.92  105.49 2320.85  107.79 2330.78  108.03
#Mann= 3 ,-1 , 0
       0     .07       0 1201.11     .04       0 1360.68     .08       0
#XS Ineff= 2 ,-1
       0 1201.11  105.49 1360.68 2330.78  106.29
Permanent Ineff=
       F       F
#Block Obstruct= 2 , 0
       0  268.85  107.38               0
Bank Sta=1201.11,1360.68
XS Rating Curve= 0 ,0
Exp/Cntr=0.3,0.1

Type RM Length L Ch R = 1 ,1081.651,50.99,49.28,49.34
XS GIS Cut Line= 6
3027715.9539351913865654.27706333027159.0439597813865194.9321814
3026796.2530186913865006.5601829 3026408.175054713864899.5279166
3025457.3190167713864883.13392053024325.23105787 13864860.828847
#Sta/Elev= 30
       0  106.38 1080.83     104 1100.77  102.31 1119.62  104.77 1135.65   104.9
 1150.56  102.65 1165.47  104.89  1309.6  105.82 1329.48  101.53  1338.3  101.17
 1354.33  103.92 1369.24  104.33 1418.94  102.62  1701.3  102.63 1916.64   101.6
 1961.45  105.02 1983.35  101.62 1983.86 99.4944 2004.64 94.4044 2017.37  100.28
 2026.18  101.89 2649.22  103.94 2799.19  105.82 3019.14  105.87 3034.14  103.94
 3044.14  105.65 3346.54  106.02 3391.62  106.15 3537.19  106.55 3616.57  108.72
#Mann= 8 ,-1 , 0
       0     .07       0 1119.62      .1       0  1338.3     .07       0
  1701.3     .12       0 1961.45     .06       0 2026.18     .12       0
 3346.54     .08       0 3391.62     .07       0
#XS Ineff= 2 ,-1
       0 1884.62  104.07 2079.47 3616.57  104.33
Permanent Ineff=
       F       F
Bank Sta=1961.45,2026.18
XS Rating Curve= 0 ,0
Exp/Cntr=0.5,0.3

Type RM Length L Ch R = 1 ,1032.373,112.59,112.51,115
BEGIN DESCRIPTION:
Upstream Section (CLAY ROAD)
END DESCRIPTION:
Node Name=B
XS GIS Cut Line= 6
3027725.7324589513865542.13096213027368.3808114413865204.6890517
3027120.2966619413865038.3478489 3026912.000818713864957.0615942
3026234.0212035313864846.84823193024313.9656604413864825.1589708
#Sta/Elev= 30
       0   105.4  447.75  103.89  551.96   104.8  790.91  102.32 1118.57  104.42
 1149.32  103.59 1169.29  105.53 1209.24  104.78 1254.18  105.95 1337.13   104.9
 1403.78  103.12 1647.36  103.65 1690.25  102.62  1938.2  102.32 1972.64  101.55
 1977.56  100.29  1983.6   96.76 1993.64    94.3  2011.9  101.58 2031.48  103.03
 2305.27  102.53 2920.09  105.27 2975.08  104.17 3005.07  105.58 3025.06  103.39
 3035.06  105.02 3060.05   105.4 3370.43  105.88 3392.04  106.02 3622.29  107.45
#Mann= 8 ,-1 , 0
       0     .07       0 1118.57      .1       0 1337.13     .07       0
 1690.25     .12       0  1938.2     .06       0 2031.48     .12       0
 3370.43     .08       0 3392.04     .07       0
#XS Ineff= 2 ,-1
       0 1946.81  104.07 2033.96 3622.29  104.33
Permanent Ineff=
       F       F
#Block Obstruct= 2 , 0
       0   19.53  106.02               0
Bank Sta=1938.2,2031.48
XS Rating Curve= 0 ,0
Exp/Cntr=0.5,0.3

Type RM Length L Ch R = 3 ,972.7242,,,
BEGIN DESCRIPTION:
CLAY ROAD
END DESCRIPTION:
Node Name=CLAY ROAD
Bridge Culvert--1,0,-1,-1, 0
Deck Dist Width WeirC Skew NumUp NumDn MinLoCord MaxHiCord MaxSubmerge Is_Ogee
10,80,2.6,0, 50, 50, , , 0.98, 0, 0,0,,
       0   97.66  122.07   185.9  195.78  294.59   393.4   497.2  601.74   701.3
  795.88  895.25  994.63  1089.4 1199.25 1299.12 1388.86 1458.46 1567.82  1692.1
 1805.36 1898.84 1899.98 1946.81 1952.73  1953.1 1978.05 2002.65 2027.04 2028.09
 2033.96 2084.31 2085.34 2130.33 2200.31 2300.28 2405.25 2500.22 2610.18 2680.16
 2785.13  2885.1 2995.07 3100.04 3193.65 3291.81 3399.89 3498.73 3558.04 3622.29
  105.93  105.88  106.39  106.26   105.7  105.44  105.06  105.32  104.93  104.72
  104.35  104.81  105.03  105.18  105.33  104.97  105.56   104.9  104.86  104.81
  104.57  104.14  104.87   106.6   108.1   108.1   108.1   108.2   108.2   108.2
   106.6   106.6  104.33  104.62  104.79  104.98  105.33  105.72  105.97  105.92
  106.09  106.26  106.76  106.92  107.01  107.05  107.55  107.91  107.96  108.63
                                                                                
                                                                                
                           103.4   103.4   103.4   103.4   103.4   103.4   103.4
   103.4
                                                                                
       0   97.66  122.07   185.9  195.78  294.59   393.4   497.2  601.74   701.3
  795.88  895.25  994.63  1089.4 1199.25 1299.12 1388.86 1458.46 1567.82  1692.1
 1805.36 1895.83 1942.66 1948.58 1948.95  1973.9  1998.5 2022.89 2023.94 2029.81
 2080.16 2080.16 2085.34 2130.33 2200.31 2300.28 2405.25 2500.22 2610.18 2680.16
 2785.13  2885.1 2995.07 3100.04 3193.65 3291.81 3399.89 3498.73 3558.04 3622.29
  105.93  105.88  106.39  106.26   105.7  105.44  105.06  105.32  104.93  104.72
  104.35  104.81  105.03  105.18  105.33  104.97  105.56   104.9  104.86  104.81
  104.57  104.87   106.6   108.1   108.1   108.1   108.2   108.2   108.2   106.6
   106.2  104.97  104.33  104.62  104.79  104.98  105.33  105.72  105.97  105.92
  106.09  106.26  106.76  106.92  107.01  107.05  107.55  107.91  107.96  108.63
                                                                                
                                                                                
                   103.4   103.4   103.4   103.4   103.4   103.4   103.4   103.4
                                                                                
                                                                                
Pier Skew, UpSta & Num, DnSta & Num=  ,1978.05, 3 ,1973.88, 3 , 3 , 3 , 0 ,,
    1.35    1.35       2
       0  101.39  103.39
    1.35    1.35       2
       0  101.39  103.39
Pier Skew, UpSta & Num, DnSta & Num=  ,2002.64, 3 ,1997.98, 3 , 3 , 3 , 0 ,,
    1.35    1.35       2
       0  101.36  103.36
    1.35    1.35       2
       0  101.36  103.36
BR Coef=-1 , 1 , 1 ,0.9, 0 ,,,0.8,0,1.2,0,
WSPro=,,,, 1 ,,,, 0 ,,,, 0 ,,,,-1 ,-1 ,-1 , 0 , 0 , 0 , 0 , 0
BR U #Sta/Elev= 30
       0   105.4  447.75  103.89  551.96   104.8  790.91  102.32 1118.57  104.42
 1149.32  103.59 1169.29  105.53 1209.24  104.78 1254.18  105.95 1337.13   104.9
 1403.78  103.12 1647.36  103.65 1690.25  102.62  1938.2  102.32 1972.64  101.55
 1977.56  100.29  1983.6   96.76 1993.64    94.3  2011.9  101.58 2031.48  103.03
 2305.27  102.53 2920.09  105.27 2975.08  104.17 3005.07  105.58 3025.06  103.39
 3035.06  105.02 3060.05   105.4 3370.43  105.88 3392.04  106.02 3622.29  107.45
BR U #Mann= 8
       0     .07 1118.57      .1 1337.13     .07 1690.25     .12  1938.2    .015
 2031.48     .12 3370.43     .08 3392.04     .07
BR D #Sta/Elev= 30
       0   105.1    70.1  104.42  122.07  105.62  131.84  103.56  151.37  103.34
  388.46  104.43  517.11  102.45  746.55  103.55  762.19  103.89  910.16  104.35
 1054.45  102.65 1069.43  104.46 1119.36  105.09 1214.51  104.26 1382.27  103.68
 1617.54  104.01 1893.92     101 1933.28  104.15  1962.8   102.8 1982.48   95.16
 1996.39   93.37    2007   95.18 2026.59  101.95 2046.17  103.66 2075.55  101.97
 2160.32   101.8 2490.22  103.88 3335.98  104.19 3414.84   105.6 3622.29  106.01
BR D #Mann= 9
       0     .07    70.1      .1  746.55     .07  762.19      .1 1214.51     .07
 1382.27     .12 1933.28    .015 2046.17     .12 3414.84     .07
BC Design=,, 0 ,, 0 ,,,,,,
BC Use User HTab Curves=0
BC User HTab FreeFlow(D)= 0

Type RM Length L Ch R = 1 ,919.8665,76.37,74.86,82.92
BEGIN DESCRIPTION:
Downstream Section (CLAY ROAD)
END DESCRIPTION:
XS GIS Cut Line= 6
3027735.6746962813865430.22567413027378.3230487713865092.7837637
3027130.2388992813864926.44256093026921.9430560313864845.1563062
3026243.9634408713864734.94294393024323.9078977713864713.2536829
#Sta/Elev= 30
       0   105.1    70.1  104.42  122.07  105.62  131.84  103.56  151.37  103.34
  388.46  104.43  517.11  102.45  746.55  103.55  762.19  103.89  910.16  104.35
 1054.45  102.65 1069.43  104.46 1119.36  105.09 1214.51  104.26 1382.27  103.68
 1617.54  104.01 1893.92     101 1933.28  104.15  1962.8   102.8 1982.48   95.16
 1996.39   93.37    2007   95.18 2026.59  101.95 2046.17  103.66 2075.55  101.97
 2160.32   101.8 2490.22  103.88 3335.98  104.19 3414.84   105.6 3622.29  106.01
#Mann= 9 ,-1 , 0
       0     .07       0    70.1      .1       0  746.55     .07       0
  762.19      .1       0 1214.51     .07       0 1382.27     .12       0
 1933.28     .04       0 2046.17     .12       0 3414.84     .07       0
#XS Ineff= 2 ,-1
       0 1957.88   103.6 2029.81 3622.29   103.6
Permanent Ineff=
       F       F
#Block Obstruct= 2 , 0
       0   97.66  105.58               0
Bank Sta=1933.28,2046.17
XS Rating Curve= 0 ,0
Exp/Cntr=0.5,0.3

Type RM Length L Ch R = 1 ,845.0081,267.53,283.74,286.75
XS GIS Cut Line= 6
3027388.2367428513864973.4831493 3026736.572035713864657.9811556
3026144.1221051113864656.36108013025645.0902947813864654.2344439
3025307.50730853 13864647.8056513024362.1542123613864675.2868953
#Sta/Elev= 30
       0  104.58  119.84  104.14  169.77   101.7  229.69  103.86  434.41  104.67
  524.29  103.51  574.36  104.72  604.18  103.08  614.17  104.48  689.07  105.49
   759.6  104.21  818.62  102.15  878.36  103.48   938.1  102.09 1346.42  101.76
 1416.28   99.47 1451.21  103.51 1476.17  104.27 1486.15  103.16 1501.12   95.43
 1510.86   93.87 1531.06   97.44 1551.02  103.01 1570.98   104.3 1630.87  101.67
 1735.66  101.78 2526.48  105.24 2725.59  103.99 2933.74   105.8 3098.91  106.43
#Mann= 6 ,-1 , 0
       0      .1       0  574.36     .07       0   759.6     .12       0
 1476.17     .04       0 1570.98     .12       0 2933.74     .07       0
#XS Ineff= 2 ,-1
       0    1347     104 1692.72 3098.91     104
Permanent Ineff=
       F       F
#Block Obstruct= 2 , 0
       0    4.99  104.69               0
Bank Sta=1476.17,1570.98
XS Rating Curve= 0 ,0
Exp/Cntr=0.3,0.1

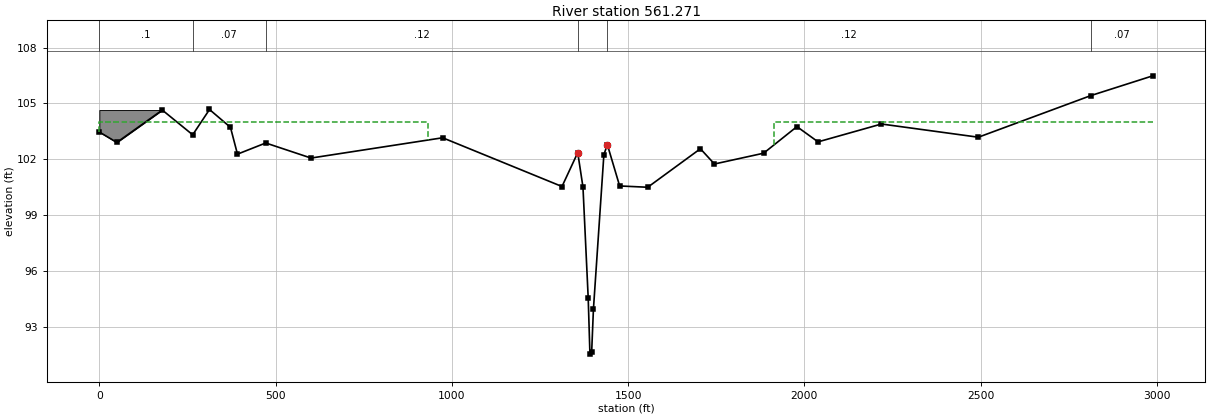
Type RM Length L Ch R = 1 ,561.271 ,0,0,0
BEGIN DESCRIPTION:
Confluence with Bear Creek (U102-00-00)
END DESCRIPTION:
Node Name=A
XS GIS Cut Line= 6
3027202.0688081113864832.3899275 3026779.439732113864545.2628771
3025970.3307860213864376.4705638 3025867.103302213864387.3363557
3025304.7500961913864408.26052643024351.2880923613864653.5549833
#Sta/Elev= 30
       0  103.46   49.61   102.9  178.58  104.64  264.85  103.31  312.52  104.67
  372.04  103.71  391.88  102.27  472.05  102.87  600.56  102.06  973.99  103.15
 1312.57  100.53 1357.24  102.35 1372.07   100.5 1386.89   94.55 1391.84   91.52
 1396.78   91.65 1401.72   93.93 1431.38  102.24 1441.26  102.78 1476.12  100.56
  1555.8  100.49 1705.21  102.56 1745.05  101.74 1884.49  102.32 1979.11  103.75
 2038.99  102.93  2218.9  103.89 2493.77  103.18 2813.27  105.42 2988.53  106.48
#Mann= 6 ,-1 , 0
       0      .1       0  264.85     .07       0  472.05     .12       0
 1357.24     .04       0 1441.26     .12       0 2813.27     .07       0
#XS Ineff= 2 ,-1
       0  932.62     104  1913.6 2988.53     104
Permanent Ineff=
       F       F
#Block Obstruct= 2 , 0
       0  178.58  104.64               0
Bank Sta=1357.24,1441.26
XS Rating Curve= 0 ,0
Exp/Cntr=0.3,0.1

Chan Stop Cuts=-1
Use User Specified Reach Order=0
Composite Channel Slope=5